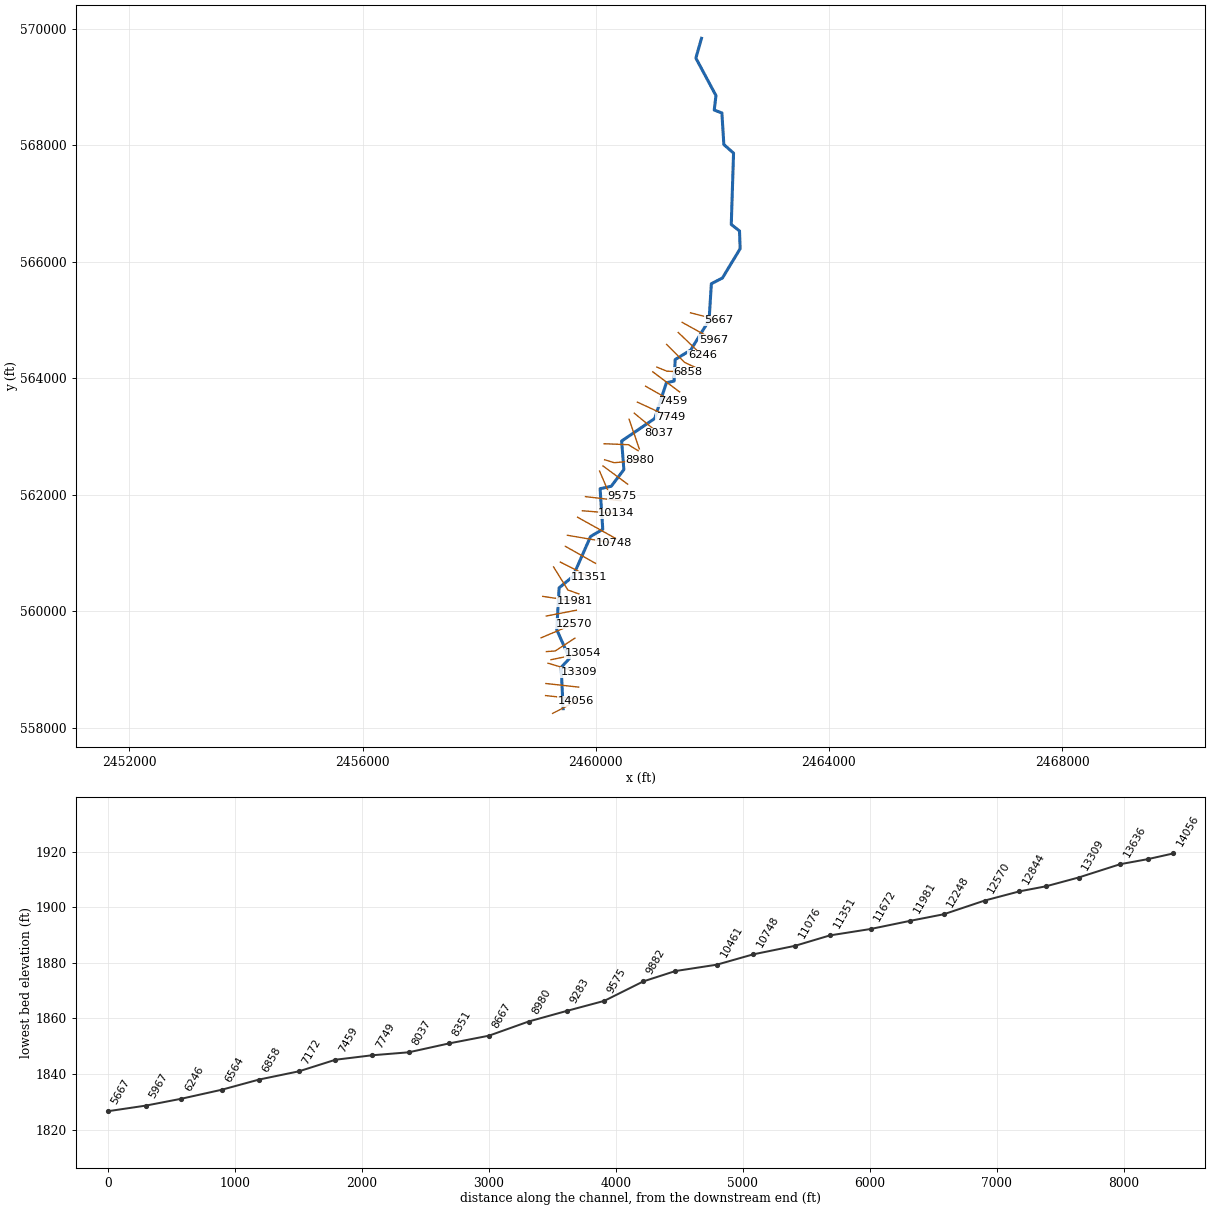
--- LICKRN.prj (project) ---

Proj Title=LICKRN
Current Plan=p01
Default Exp/Contr=0,0
English Units
Geom File=g01
Flow File=f01
Plan File=p01
BEGIN DESCRIPTION:
Stream Name: Lick Run
Flood Zone: Approximate
Pendleton County, West Virginia
HEC-RAS Version: 5.0.7
Hydrology Method:
Regression equation
END DESCRIPTION:
DSS Export Rating Curves= 0
DSS Export Rating Curve Sorted= 0
DSS Export Volume Flow Curves= 0
DXF OffsetX= 0
DXF OffsetY= 0
DXF ScaleX= 0
DXF ScaleY= 0

--- LICKRN.p01 (plan) ---

Plan Title=Floodplain
Program Version=5.07
Short Identifier=Floodplain
Geom File=g01
Flow File=f01
Subcritical Flow
K Sum by GR= 0
Std Step Tol= 0.01
Critical Tol= 0.01
Num of Std Step Trials= 20
Max Error Tol= 0.3
Flow Tol Ratio= 0.001
Split Flow NTrial= 30
Split Flow Tol= 0.02
Split Flow Ratio= 0.02
Log Output Level= 0
Friction Slope Method= 1
Unsteady Friction Slope Method= 2
Unsteady Bridges Friction Slope Method= 1
Parabolic Critical Depth
Global Vel Dist= 0 , 0 , 0
Global Log Level= 0
CheckData=True
Encroach Param=-1 ,0,0, 0
Mapping Interval=1HOUR
Computation Time Step Use Courant=        0
Computation Time Step Use Time Series=    0
Computation Time Step Count To Double=0
Computation Time Step Max Doubling=0
Computation Time Step Max Halving=0
Computation Time Step Residence Courant=0
Run HTab= 0
Run UNet= 0
Run Sediment= 0
Run PostProcess= 0
Run WQNet= 0
Run RASMapper= 0
UNET Theta= 0
UNET Theta Warmup= 0
UNET ZTol= 0
UNET ZSATol= 0
UNET MxIter= 0
UNET Max Iter WO Improvement= 0
UNET MaxInSteps= 0
UNET DtIC= 0
UNET DtMin= 0
UNET MaxCRTS= 0
UNET WFStab= 0
UNET SFStab= 0
UNET WFX= 1
UNET SFX= 1
UNET 1D Methodology=Finite Difference
UNET DSS MLevel= 1
UNET Pardiso=0
UNET DZMax Abort= 0
UNET Use Existing IB Tables= 0
UNET Froude Reduction=False
UNET Froude Limit= 0
UNET Froude Power= 0
UNET D1 Cores= 0
UNET D2 Coriolis=0
UNET D2 Cores= 0
UNET D2 Theta= 1
UNET D2 Theta Warmup= 1
UNET D2 Z Tol= 0.01
UNET D2 Volume Tol= 0.01
UNET D2 Max Iterations= 20
UNET D2 Equation= 0
UNET D2 RampUpFraction=0.1
UNET D2 TimeSlices= 1
UNET D2 BCVolumeCheck=0
UNET D1D2 MaxIter= 0
UNET D1D2 ZTol=0.01
UNET D1D2 QTol=0.1
UNET D1D2 MinQTol=1
Write IC File= 0
Write IC File at Fixed DateTime=0
Write IC File at Sim End=0
Echo Input=False
Echo Parameters=False
Echo Output=False
Write Detailed= 0
HDF Write Warmup=0
HDF Write Time Slices=0
HDF Flush=0
HDF Face Node Velocities=0
HDF Compression= 1
HDF Chunk Size= 1
HDF Spatial Parts= 1
HDF Use Max Rows=0
HDF Fixed Rows= 1
Calibration Method= 0
Calibration Iterations= 20
Calibration Max Change=0.05
Calibration Tolerance=0.2
Calibration Maximum=1.5
Calibration Minimum=0.5
Calibration Optimization Method= 1
WQ AD Non Conservative
WQ ULTIMATE=-1
WQ Max Comp Step=1HOUR
WQ Output Interval=15MIN
WQ Output Selected Increments= 0
WQ Output face flow=0
WQ Output face velocity=0
WQ Output face area=0
WQ Output face dispersion=0
WQ Output cell volume=0
WQ Output cell surface area=0
WQ Output cell continuity=0
WQ Output cumulative cell continuity=0
WQ Output face conc=0
WQ Output face dconc_dx=0
WQ Output face courant=0
WQ Output face peclet=0
WQ Output face adv mass=0
WQ Output face disp mass=0
WQ Output cell mass=0
WQ Output cell source sink temp=0
WQ Output nsm pathways=0
WQ Output nsm derived pathways=0
WQ Output MaxMinRange=-1
WQ Daily Max Min Mean=-1
WQ Daily Range=0
WQ Daily Time=0
WQ Create Restart=0
WQ Fixed Restart=0
WQ System Summary=0
WQ Write To DSS=0
WQ Use Fixed Temperature=0
Sorting and Armoring Iterations= 10
XS Update Threshold= 0.02
Bed Roughness Predictor= 0
Hydraulics Update Threshold= 0.02
Energy Slope Method= 1
Volume Change Method= 1
Sediment Retention Method= 0
XS Weighting Method= 0
Number of US Weighted Cross Sections= 1
Number of DS Weighted Cross Sections= 1
Upstream XS Weight=0
Main XS Weight=1
Downstream XS Weight=0
Number of DS XS's Weighted with US Boundary= 1
Upstream Boundary Weight= 1
Weight of XSs Associated with US Boundary= 0
Number of US XS's Weighted with DS Boundary= 1
Downstream Boundary Weight= 0.5
Weight of XSs Associated with DS Boundary= 0.5
Percentile Method= 0
Sediment Output Level= 3
Mass or Volume Output= 0
Output Increment Type= 1
Profile and TS Output Increment= 1
XS Output Flag= 0
XS Output Increment= 10
Write Gradation File= 0
Read Gradation Hotstart= 0
Write HDF5 File= 1
Write Binary Output= 1
Write DSS Sediment File= 0
SV Curve= 0
Specific Gage Flag= 0

--- LICKRN.f01 (steady flow) ---

Flow Title=Flows
Program Version=5.07
Number of Profiles= 6
Profile Names=P100yr,P10yr,P25yr,P50yr,P500yr,P101yr
River Rch & RM=LICKRN,Main            ,14056
     614     287     406     507     901     747
River Rch & RM=LICKRN,Main            ,10134
     749     349     494     617    1100     911
River Rch & RM=LICKRN,Main            ,5967
     836     389     551     689    1230    1017
Boundary for River Rch & Prof#=LICKRN,Main            , 1
Up Type= 0
Dn Type= 3
Dn Slope=0.00785
Boundary for River Rch & Prof#=LICKRN,Main            , 2
Up Type= 0
Dn Type= 3
Dn Slope=0.00785
Boundary for River Rch & Prof#=LICKRN,Main            , 3
Up Type= 0
Dn Type= 3
Dn Slope=0.00785
Boundary for River Rch & Prof#=LICKRN,Main            , 4
Up Type= 0
Dn Type= 3
Dn Slope=0.00785
Boundary for River Rch & Prof#=LICKRN,Main            , 5
Up Type= 0
Dn Type= 3
Dn Slope=0.00785
Boundary for River Rch & Prof#=LICKRN,Main            , 6
Up Type= 0
Dn Type= 3
Dn Slope=0.00785
DSS Import GetInterval= 0
DSS Import GetPeak= 0
DSS Import FillOption= 0

--- LICKRN.g01 (geometry) ---

Geom Title=Geometry
Program Version=5.07

River Reach=LICKRN          ,Main
Reach XY= 30
     2459440.208       558329.86     2459406.771      559038.182
     2459550.195      559194.512     2459330.129      559687.511
     2459371.767       560403.73     2459608.616      560600.362
     2459910.874        561285.8     2460120.353      561409.271
     2460074.683      562105.544     2460266.243      562148.751
     2460482.451      562434.485     2460443.963      562924.285
     2461011.328      563311.413     2461211.844      563924.868
     2461343.885      563953.515     2461362.637      564322.805
     2461628.427      564486.414     2461943.869      564998.274
     2461983.027      565624.418     2462173.328      565723.911
     2462476.766      566226.111     2462465.941      566531.196
     2462324.547      566642.502     2462363.859      567866.768
     2462197.116      568014.787     2462163.877      568557.076
     2462032.383      568605.996     2462062.058      568854.653
     2461717.571      569498.339     2461813.917      569837.576

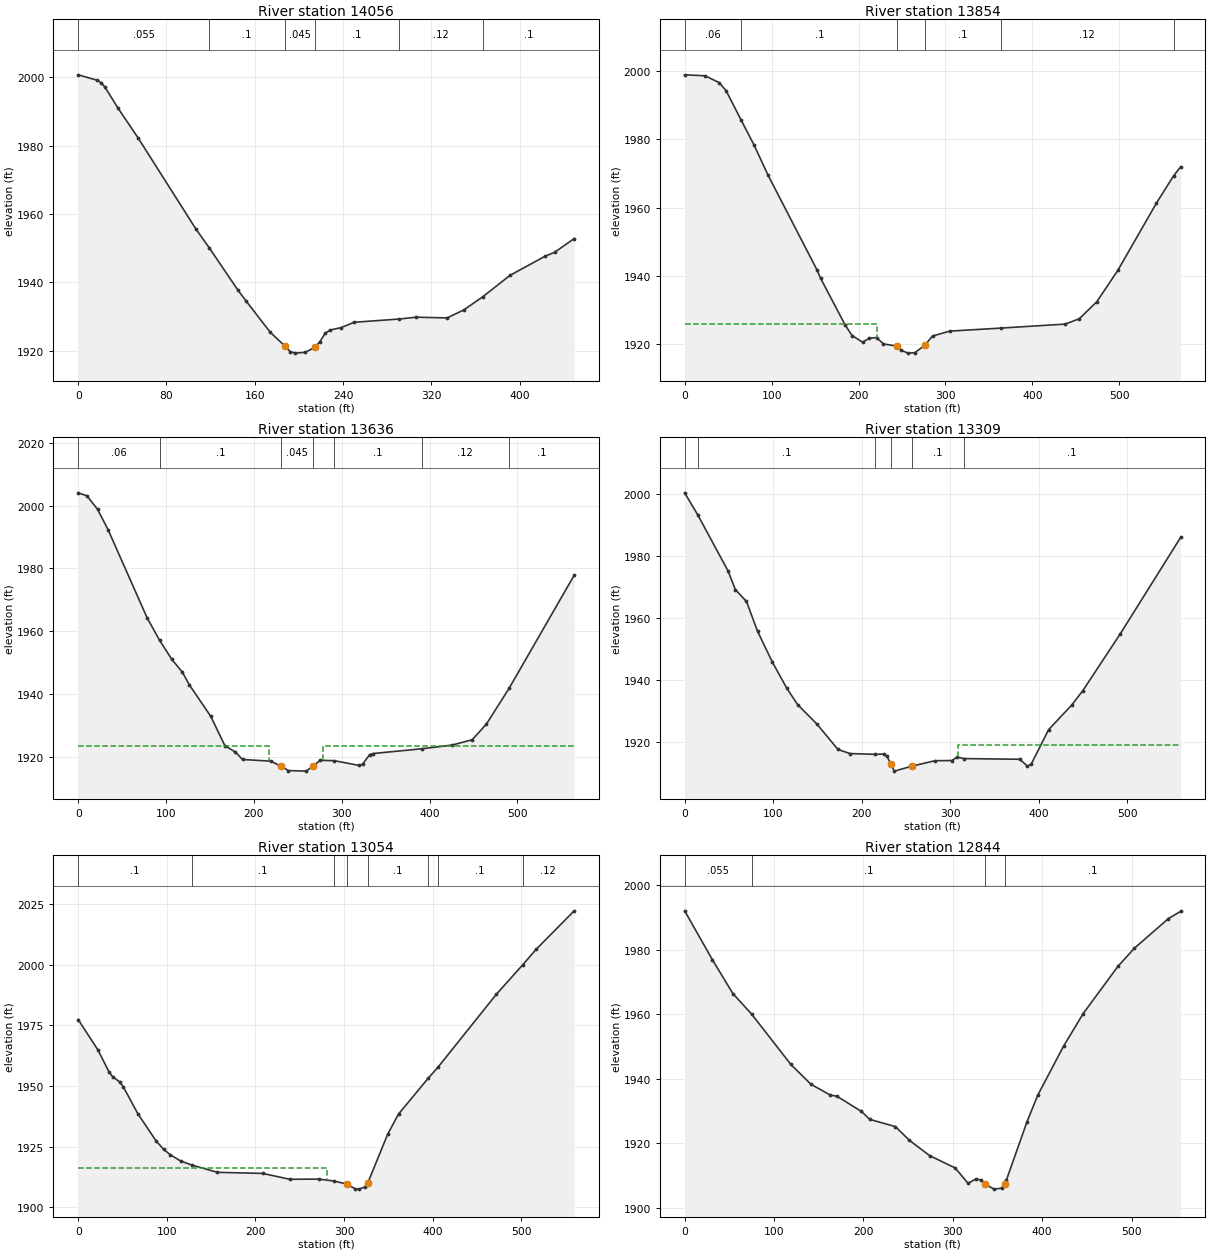
Type RM Length L Ch R = 1 ,14056   ,201.7,201.7,201.7
XS GIS Cut Line= 3
2459259.47715245558249.463810283     2459435.694      558338.784
2459658.27040121558456.819978222
#Sta/Elev= 30
       0  2000.7    17.1 1999.12    20.9 1998.39    24.3 1997.07    36.2  1990.9
    54.1 1982.35   106.8 1955.56  118.751950.137   144.7 1937.78   152.3 1934.52
   174.1 1925.42   187.5 1921.37     192 1919.81   196.5 1919.34   205.8 1919.58
   214.7 1921.07   219.1  1922.7   223.7 1925.09   228.2 1926.07   238.4 1926.82
   250.2 1928.36  290.45  1929.3   306.4 1929.84   334.4 1929.64   349.3 1931.94
  366.861935.854   391.2 1942.04   422.9 1947.63   431.9 1948.83   449.5 1952.83
#Mann= 6 ,-1 , 0
       0    .055       0  118.75      .1       0   187.5    .045       0
   214.7      .1       0  290.45     .12       0  366.86      .1       0
Bank Sta=187.5,214.7
XS Rating Curve= 0 ,0
Exp/Cntr=0.3,0.1

Type RM Length L Ch R = 1 ,13854   ,218,218,218
XS GIS Cut Line= 2
2459139.27266255558554.9357667272459706.58131724558494.990041985
#Sta/Elev= 30
       0 1998.93    23.6 1998.65    39.7 1996.63    47.7 1994.26   64.97 1985.63
    79.6 1978.45      96 1969.44   152.3 1941.65   156.3 1939.26   184.5 1925.58
   192.5 1922.45   204.6 1920.51   212.6 1921.65   220.7 1921.85   228.7 1919.97
   244.8 1919.32   248.9 1918.13   256.9 1917.28   264.9 1917.43     276 1919.55
   285.1  1922.3     305 1923.74  363.381924.618   437.9  1925.8     454 1927.38
   474.1 1932.37   498.2 1941.53   542.5 1961.22  562.321969.276   570.5 1971.92
#Mann= 6 ,-1 , 0
       0     .06       0   64.97      .1       0   244.8    .045       0
     276      .1       0  363.38     .12       0  562.32      .1       0
#XS Ineff= 2 , 0
          220.84 1925.73
Permanent Ineff=
       F       F
Bank Sta=244.8,276
XS Rating Curve= 0 ,0
Exp/Cntr=0.3,0.1

Type RM Length L Ch R = 1 ,13636   ,327.3,327.3,327.3
XS GIS Cut Line= 2
2459144.86238572558761.706275258  2459706.067381558700.644127526
#Sta/Elev= 30
       0 2004.05     9.9 2003.11      22 1998.81    34.1 1992.24    78.3 1964.34
   92.581957.128   106.5 1951.06   118.6 1946.94   126.6 1942.88   150.8 1932.94
   166.9 1923.58   178.9 1921.53     187 1919.17   219.2 1918.64   231.2 1916.97
   239.3 1915.64   259.4 1915.46   267.31917.046   275.5 1918.91  291.491918.783
   319.8 1917.27   323.8 1917.72   331.8 1920.72   335.9 1921.07  390.941922.572
   425.2 1923.73   448.5 1925.45   464.6 1930.42  490.391941.793   564.5 1977.79
#Mann= 7 ,-1 , 0
       0     .06       0   92.58      .1       0   231.2    .045       0
   267.3      .1       0  291.49      .1       0  390.94     .12       0
  490.39      .1       0
#XS Ineff= 2 , 0
          217.34 1923.53  279.07         1923.53
Permanent Ineff=
       F       F
Bank Sta=231.2,267.3
XS Rating Curve= 0 ,0
Exp/Cntr=0.3,0.1

Type RM Length L Ch R = 1 ,13309   ,255.1,255.1,255.1
XS GIS Cut Line= 2
 2459179.8152582559111.2483607992459716.71289111558951.560639201
#Sta/Elev= 30
       0 2000.35    14.71993.271      49 1975.17    57.3 1969.15    69.8 1965.34
    82.3 1955.74      99 1945.82   115.2 1937.45   127.5 1932.12   149.1 1925.92
   173.1 1917.66   186.7 1916.33  214.981916.092   224.6 1916.16   228.4 1915.43
   232.6 1913.11   236.8 1910.67   256.7 1912.28   282.7 1914.03   301.8 1914.08
   307.7 1915.22  315.121914.717   378.6 1914.49     387 1912.28   391.2 1912.84
   411.1 1924.06   437.1 1931.96   449.6 1936.58   491.6 1954.76   560.1 1985.98
#Mann= 6 ,-1 , 0
       0     .06       0    14.7      .1       0  214.98      .1       0
   232.6    .045       0   256.7      .1       0  315.12      .1       0
#XS Ineff= 2 , 0
                          308.22         1919.01
Permanent Ineff=
       F       F
Bank Sta=232.6,256.7
XS Rating Curve= 0 ,0
Exp/Cntr=0.3,0.1

Type RM Length L Ch R = 1 ,13054   ,209.8,209.8,209.8
XS GIS Cut Line= 2
 2459232.8774075 559170.755976652459780.85916794559284.256231701
#Sta/Elev= 30
       0 1977.38    22.3 1964.86    34.6 1955.92    38.7 1953.89    46.8 1951.72
    50.9 1949.68    67.3 1938.59    87.7 1927.49    96.4 1923.91     104 1921.68
   115.6 1919.12  127.831917.499   157.1 1914.46   208.1    1914   238.8 1911.59
   271.5 1911.66  288.691910.868   302.9 1909.64   312.4 1907.66   316.4 1907.53
   323.2 1908.36   326.6 1909.94   349.1 1930.06   361.4 1938.46  395.011953.251
  405.931957.763   471.7 1987.76  501.331999.864   516.6 2006.29   559.6 2022.21
#Mann= 8 ,-1 , 0
       0      .1       0  127.83      .1       0  288.69      .1       0
   302.9    .045       0   326.6      .1       0  395.01     .12       0
  405.93      .1       0  501.33     .12       0
#XS Ineff= 2 , 0
          280.25 1916.33
Permanent Ineff=
       F       F
Bank Sta=302.9,326.6
XS Rating Curve= 0 ,0
Exp/Cntr=0.3,0.1

Type RM Length L Ch R = 1 ,12844   ,274.1,274.1,274.1
XS GIS Cut Line= 3
2459153.00915088 559310.015723172459303.51852874559320.267721598
2459642.15540121559540.662444768
#Sta/Elev= 30
       0 1992.02      31 1976.85    53.9 1966.37    74.8 1960.03   118.8 1944.37
   141.3 1938.22     163 1934.86   170.3 1934.52   197.7 1929.81   207.2 1927.32
   235.8  1925.1     251 1920.94     274  1916.1   302.7 1912.26     317 1907.53
   326.5 1908.92   331.3 1908.46   336.1 1907.23   346.3  1905.7   354.6    1906
   357.9 1907.42   359.9 1908.47     383 1926.57     395 1934.81   423.9 1950.03
   445.8 1960.12   484.7 1974.77   503.1  1980.4   541.3 1989.63   554.9 1991.85
#Mann= 4 ,-1 , 0
       0    .055       0    74.8      .1       0   336.1    .045       0
   357.9      .1       0
Bank Sta=336.1,357.9
XS Rating Curve= 0 ,0
Exp/Cntr=0.3,0.1

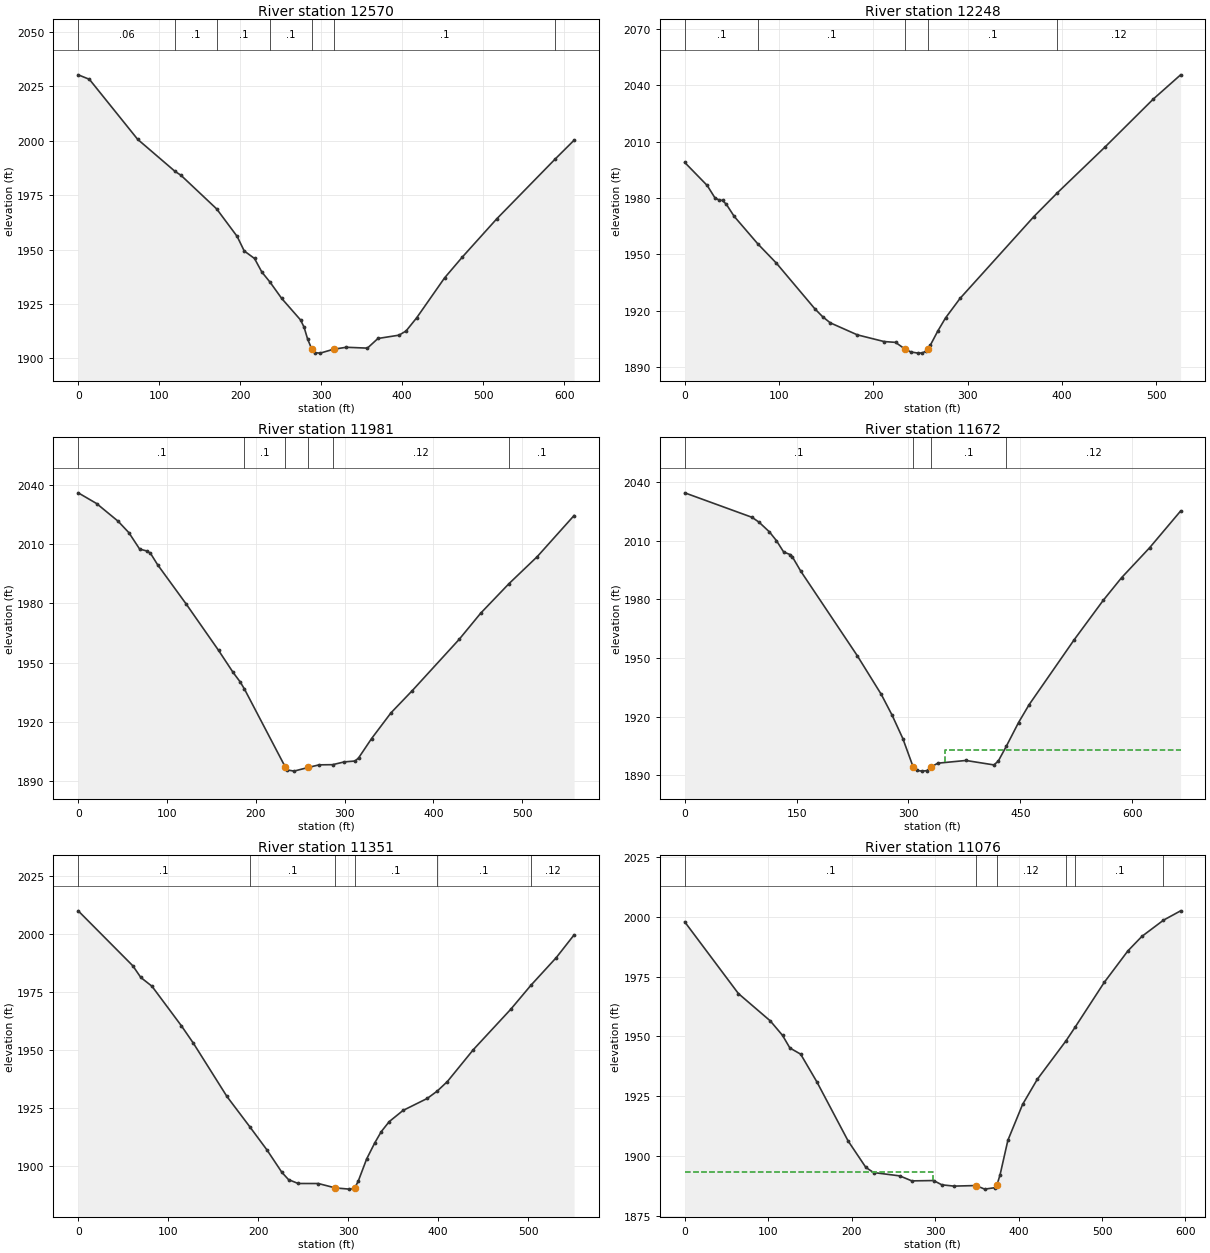
Type RM Length L Ch R = 1 ,12570   ,321.9,321.9,321.9
XS GIS Cut Line= 2
2459062.00242771559546.2263188152459625.65061428559785.308043557
#Sta/Elev= 30
       0 2030.29    13.8 2028.23    73.4 2000.65  119.561985.916   126.8 1984.15
     1711968.654   196.3    1956     205 1949.34   217.7 1945.88   226.8 1939.63
  236.921934.977   251.2 1927.55   274.5 1917.65   278.9  1914.3   283.2 1908.93
   288.5 1904.15   291.9 1902.61   298.8 1902.39   315.3 1904.18     331 1905.08
   357.1 1904.69   370.1 1909.12   396.2 1910.65   404.9  1912.6   417.9 1918.61
   452.4 1936.98   474.4 1946.58   516.7 1964.07  589.021991.624   612.3 2000.24
#Mann= 7 ,-1 , 0
       0     .06       0  119.56      .1       0     171      .1       0
  236.92      .1       0   288.5    .045       0   315.3      .1       0
  589.02     .12       0
Bank Sta=288.5,315.3
XS Rating Curve= 0 ,0
Exp/Cntr=0.3,0.1

Type RM Length L Ch R = 1 ,12248   ,267.1,267.1,267.1
XS GIS Cut Line= 2
2459151.33533588559920.1017013922459667.32269982560020.456914459
#Sta/Elev= 30
       0 1998.88    23.8 1986.63      32 1980.06    36.1 1978.94    40.1 1978.65
    44.2 1976.55    52.4 1970.21   77.621955.493    97.2  1945.3   137.9 1921.06
   146.1 1916.88   154.2  1913.6   182.9  1907.2   211.3 1903.63   223.5 1903.19
   233.5 1899.62   239.8 1898.07   247.5 1897.47     252 1897.58   256.1 1898.65
  257.67 1899.93   260.2 1901.53   268.3 1909.25   276.5  1916.2   291.8 1926.53
   370.2 1970.12  395.131982.781   445.4 2007.01   496.5 2032.47   525.7 2045.47
#Mann= 5 ,-1 , 0
       0      .1       0   77.62      .1       0   233.5    .045       0
  257.67      .1       0  395.13     .12       0
Bank Sta=233.5,257.67
XS Rating Curve= 0 ,0
Exp/Cntr=0.3,0.1

Type RM Length L Ch R = 1 ,11981   ,308.9,308.9,308.9
XS GIS Cut Line= 2
2459090.26385384560258.0374027842459642.78189111560175.685744948
#Sta/Elev= 30
       0 2035.98    20.7 2030.56      45 2021.58    57.1 2015.79    69.2 2007.51
    77.3 2006.53    81.4 2005.37    89.5 1999.53   121.8 1979.58   158.1 1956.22
   174.4 1945.11   182.5 1940.22  187.231936.667   233.41897.041     235 1895.74
   243.1 1895.08   259.3 1896.96   271.4 1898.26  286.551898.342   299.8 1899.76
   311.9  1900.2   315.9 1901.81   330.5 1911.58   352.3 1924.58   376.3 1935.83
   429.1 1961.77   453.4 1975.05   485.21989.971   517.1 2003.68   558.6  2024.5
#Mann= 6 ,-1 , 0
       0      .1       0  187.23      .1       0   233.4    .045       0
   259.3      .1       0  286.55     .12       0   485.2      .1       0
Bank Sta=233.4,259.3
XS Rating Curve= 0 ,0
Exp/Cntr=0.3,0.1

Type RM Length L Ch R = 1 ,11672   ,320.9,320.9,320.9
XS GIS Cut Line= 3
2459276.59332281560763.4546428462459522.25081457560366.742574158
2459709.38155768560301.105712921
#Sta/Elev= 30
       0 2034.53    90.1 2022.02    99.5 2019.56   113.6 2014.53     123 2010.05
   132.7 2004.24   141.4 2002.95   144.3  2001.8   155.7 1994.38   231.2  1951.3
   263.5 1931.44     278 1920.81   292.4 1908.86   306.5 1894.07   311.2  1892.5
   318.7 1892.17   324.5 1892.42   330.8 1894.43   339.4 1896.23     377 1897.62
   414.6 1895.35   420.4 1897.31  431.281904.965   447.6 1917.04   461.7 1926.14
   522.2 1959.39     561 1979.47   585.8 1991.15   623.3 2006.43   664.9 2025.24
#Mann= 4 ,-1 , 0
       0      .1       0   306.5    .045       0   330.8      .1       0
  431.28     .12       0
#XS Ineff= 2 , 0
                          349.08         1903.18
Permanent Ineff=
       F       F
Bank Sta=306.5,330.8
XS Rating Curve= 0 ,0
Exp/Cntr=0.3,0.1

Type RM Length L Ch R = 1 ,11351   ,275.2,275.2,275.2
XS GIS Cut Line= 2
 2459392.5921882560846.8880837832459884.49498075560598.180916217
#Sta/Elev= 30
       0 2009.92    60.7 1986.21    69.6 1981.17      82 1977.38   114.7 1960.32
   127.9 1952.88   165.3 1929.84   190.61916.829     210 1906.66   226.5 1897.04
   233.8 1893.96   244.5 1892.29   266.9 1892.28   285.9 1890.37   301.4 1889.86
   307.2 1890.24   311.2 1893.23   320.6 1902.86   329.6 1909.78   336.9 1914.69
   345.7 1918.98     361 1923.79   387.9 1928.97     3991932.131   410.3 1936.25
   439.2 1950.03   480.9  1967.5   503.2  1977.8   531.3  1989.7   551.2 1999.54
#Mann= 6 ,-1 , 0
       0      .1       0   190.6      .1       0   285.9    .045       0
   307.2      .1       0     399      .1       0   503.2     .12       0
Bank Sta=285.9,307.2
XS Rating Curve= 0 ,0
Exp/Cntr=0.3,0.1

Type RM Length L Ch R = 1 ,11076   ,328.4,328.4,328.4
XS GIS Cut Line= 2
2459477.88454258561117.6973887272459995.11859064560825.157001386
#Sta/Elev= 30
       0 1997.91    64.3 1967.92   102.5 1956.49   117.2 1950.42     126 1945.15
   138.9 1942.57   158.3    1931   195.8 1906.24     217 1895.21   226.2 1893.05
   257.6 1891.65   272.1 1889.56   298.2  1889.7     308 1887.92   322.6 1887.37
   349.1 1887.61   359.4 1886.11   371.3 1886.69  374.02 1887.77   377.8 1892.03
   387.2 1906.53   404.8 1921.52   422.4 1932.02  456.671948.062  467.771953.859
   502.6 1972.56     531 1985.77   547.8 1991.84  573.651998.619   594.2 2002.53
#Mann= 6 ,-1 , 0
       0      .1       0   349.1    .045       0  374.02     .12       0
  456.67      .1       0  467.77      .1       0  573.65     .12       0
#XS Ineff= 2 , 0
          297.74 1893.36
Permanent Ineff=
       F       F
Bank Sta=349.1,374.02
XS Rating Curve= 0 ,0
Exp/Cntr=0.3,0.1

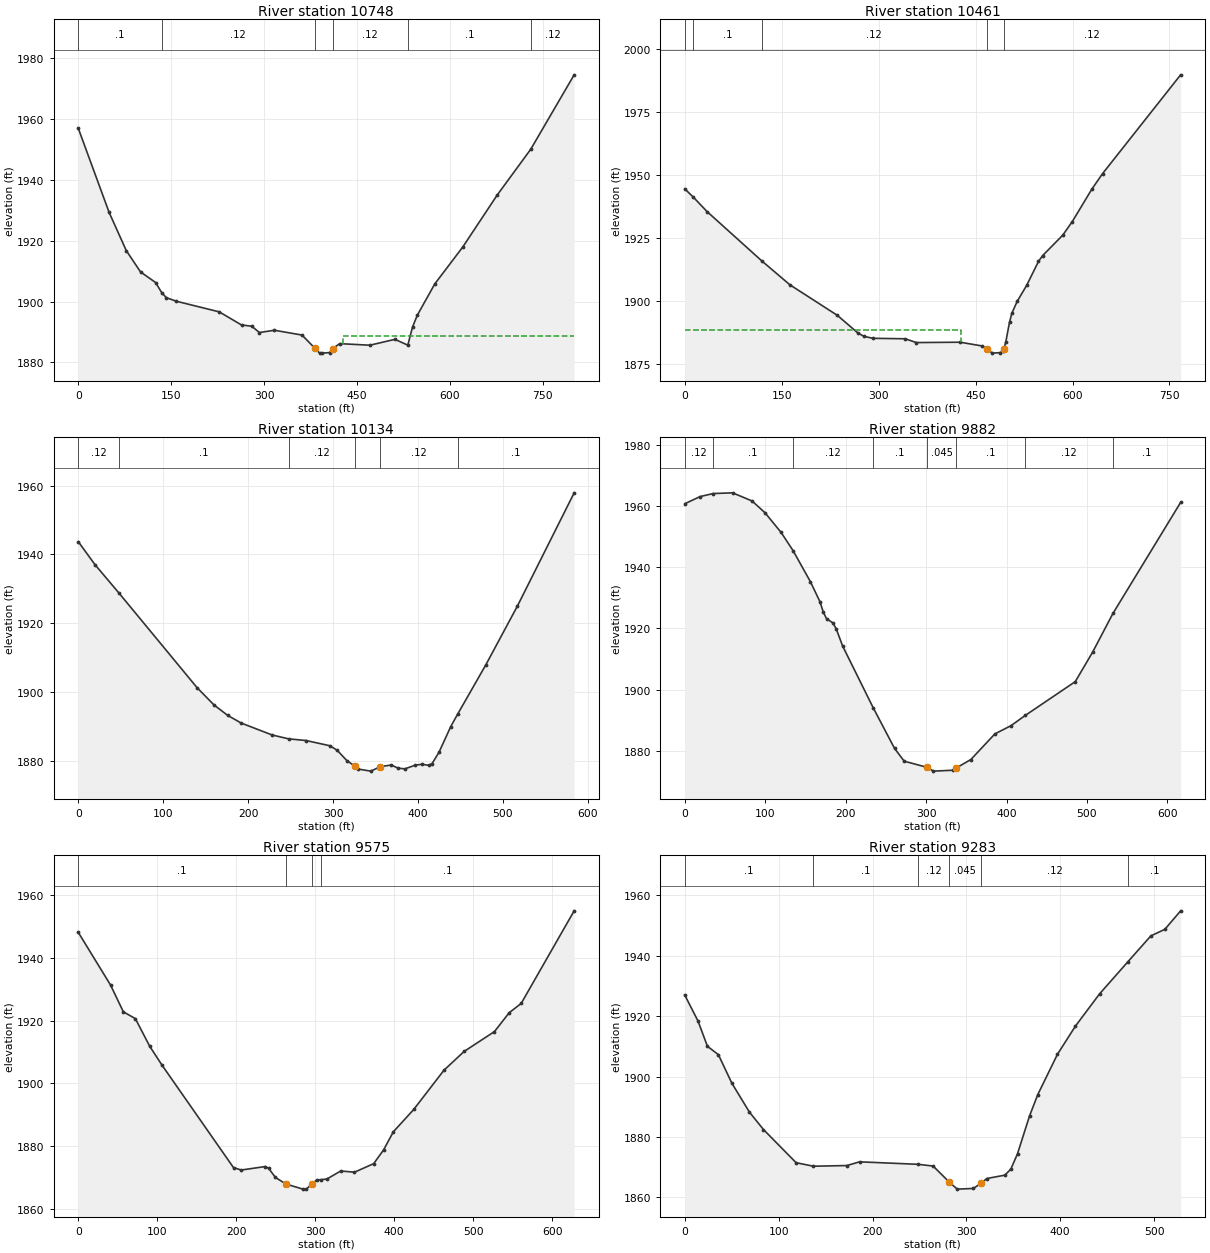
Type RM Length L Ch R = 1 ,10748   ,286.2,286.2,286.2
XS GIS Cut Line= 2
2459514.46054258561306.4606785772460304.12162775561172.901630524
#Sta/Elev= 30
       0 1956.91    49.7 1929.32    77.4 1916.77   100.5 1909.74   124.8 1906.26
  134.931902.849   142.3 1901.27   158.5  1900.1   227.5 1896.62   263.6 1892.31
   280.2 1891.89   292.4 1889.82   316.7 1890.57   361.3 1888.99   381.6 1884.76
   389.7 1883.07   393.8 1883.05     406 1883.23     411 1884.56   422.2 1886.17
   470.9 1885.65   511.4 1887.58  532.21 1885.67   539.8 1891.62   547.7 1895.58
   575.9 1905.84     621 1917.94   676.5 1934.99  730.85 1950.09   800.9 1974.53
#Mann= 6 ,-1 , 0
       0      .1       0  134.93     .12       0   381.6    .045       0
     411     .12       0  532.21      .1       0  730.85     .12       0
#XS Ineff= 2 , 0
                          426.83         1888.69
Permanent Ineff=
       F       F
Bank Sta=381.6,411
XS Rating Curve= 0 ,0
Exp/Cntr=0.3,0.1

Type RM Length L Ch R = 1 ,10461   ,327.4,327.4,327.4
XS GIS Cut Line= 2
2459688.70159341561616.488203296 2460358.9195412561242.836204682
#Sta/Elev= 30
       0 1944.52   13.35  1941.2    34.4 1935.53     119 1915.97   162.6 1906.46
   235.9 1894.36     268 1887.31   277.1 1886.02   290.9 1885.22   340.8 1885.04
   358.5 1883.53   426.1 1883.67   460.3 1882.18   467.3 1880.97   476.1 1879.34
   487.8 1879.53   492.4 1880.16   493.7 1880.98   496.7 1883.71   502.5 1891.58
   506.1 1895.13   514.3 1899.85     529 1906.21   547.3 1915.71   553.6 1918.01
   584.9 1926.15   599.6 1931.52   629.7 1944.33   646.6 1950.61   767.3 1989.78
#Mann= 5 ,-1 , 0
       0      .1       0   13.35      .1       0     119     .12       0
   467.3    .045       0   493.7     .12       0
#XS Ineff= 2 , 0
          427.61 1888.62
Permanent Ineff=
       F       F
Bank Sta=467.3,493.7
XS Rating Curve= 0 ,0
Exp/Cntr=0.3,0.1

Type RM Length L Ch R = 1 ,10134   ,251.7,251.7,251.7
XS GIS Cut Line= 2
2459771.28710303561727.3371359922460353.53779393561681.675796704
#Sta/Elev= 30
       0  1943.7    19.5 1937.08   48.261928.669   139.9 1901.28   159.9 1896.25
     176 1893.22     192 1890.99   228.2 1887.55  247.571886.422   268.3 1885.93
   296.4 1884.41     305 1883.07   316.4 1880.07   325.5 1878.53   329.8 1877.63
   344.5 1877.04   355.9 1878.36   368.6 1878.81   376.6 1877.91   384.6  1877.7
   396.7 1878.76   404.7 1879.04   412.7 1878.73   416.6 1879.21   424.8 1882.52
   438.6 1889.96  446.881893.647   479.9  1907.9   517.1 1924.98     584 1957.91
#Mann= 6 ,-1 , 0
       0     .12       0   48.26      .1       0  247.57     .12       0
   325.5    .045       0   355.9     .12       0  446.88      .1       0
Bank Sta=325.5,355.9
XS Rating Curve= 0 ,0
Exp/Cntr=0.3,0.1

Type RM Length L Ch R = 1 ,9882    ,307,307,307
XS GIS Cut Line= 2
2459823.74347667561970.4519326972460436.08810026561898.824103034
#Sta/Elev= 30
       0 1960.74    19.1 1963.09   35.261964.071    59.4 1964.31    83.6 1961.65
    99.7 1957.81   119.8 1951.34  134.67 1945.39   156.1  1935.3   168.1 1928.68
   172.2 1925.31   176.2 1923.17   184.2 1921.77   188.3 1919.81   196.3 1914.19
  234.091894.118   260.8 1880.75   272.8 1876.57   301.6 1874.54   309.1 1873.32
   333.3 1873.61   337.6 1874.36   355.7 1877.12   385.6  1885.5   405.7  1888.2
  423.211891.509   485.5 1902.58   507.1 1912.23  532.331924.873   616.5 1961.17
#Mann= 8 ,-1 , 0
       0     .12       0   35.26      .1       0  134.67     .12       0
  234.09      .1       0   301.6    .045       0   337.6      .1       0
  423.21     .12       0  532.33      .1       0
Bank Sta=301.6,337.6
XS Rating Curve= 0 ,0
Exp/Cntr=0.3,0.1

Type RM Length L Ch R = 1 ,9575    ,292.7,292.7,292.7
XS GIS Cut Line= 3
2460065.39069644562408.3536593262460210.77254258562068.763541199
2460453.83730356561980.647086554
#Sta/Elev= 30
       0 1948.07    40.8 1931.32      57  1922.8    72.2 1920.63    90.5 1911.78
     106  1905.8   196.5 1873.18   206.3 1872.41   236.6 1873.52   240.9 1872.99
   249.6 1870.05   262.7 1867.98   284.4 1866.33   288.8 1866.34  295.61 1867.94
   301.8 1869.24  307.551869.335   314.9 1869.56   332.3 1872.11   349.7 1871.72
     374 1874.44   386.5 1878.79   398.9 1884.58   424.7 1891.69     463 1904.19
   488.5 1910.17     527 1916.51   545.7 1922.53   560.8 1925.46   627.9 1954.96
#Mann= 4 ,-1 , 0
       0      .1       0   262.7    .045       0  295.61      .1       0
  307.55      .1       0
Bank Sta=262.7,295.61
XS Rating Curve= 0 ,0
Exp/Cntr=0.3,0.1

Type RM Length L Ch R = 1 ,9283    ,302.9,302.9,302.9
XS GIS Cut Line= 2
2460123.37549315 562497.559693672460548.28813322562183.590086554
#Sta/Elev= 30
       0 1926.93    14.1 1918.33    24.1    1910    35.8 1907.22    50.1 1897.81
    68.8 1888.25    83.8 1882.47   118.6 1871.49  136.98 1870.33   172.8 1870.55
   186.2 1871.78  248.691870.953   264.6 1870.38   281.8 1865.08   290.3 1862.75
   307.5 1862.97   316.1 1864.79   321.8 1866.26     341 1867.37   347.4 1869.37
   354.5 1874.45   367.3 1886.94   376.1 1894.02   397.1 1907.37   416.2 1916.66
   441.9 1927.32  472.131937.957   496.6 1946.52   511.5 1948.68   528.3  1954.8
#Mann= 6 ,-1 , 0
       0      .1       0  136.98      .1       0  248.69     .12       0
   281.8    .045       0   316.1     .12       0  472.13      .1       0
Bank Sta=281.8,316.1
XS Rating Curve= 0 ,0
Exp/Cntr=0.3,0.1

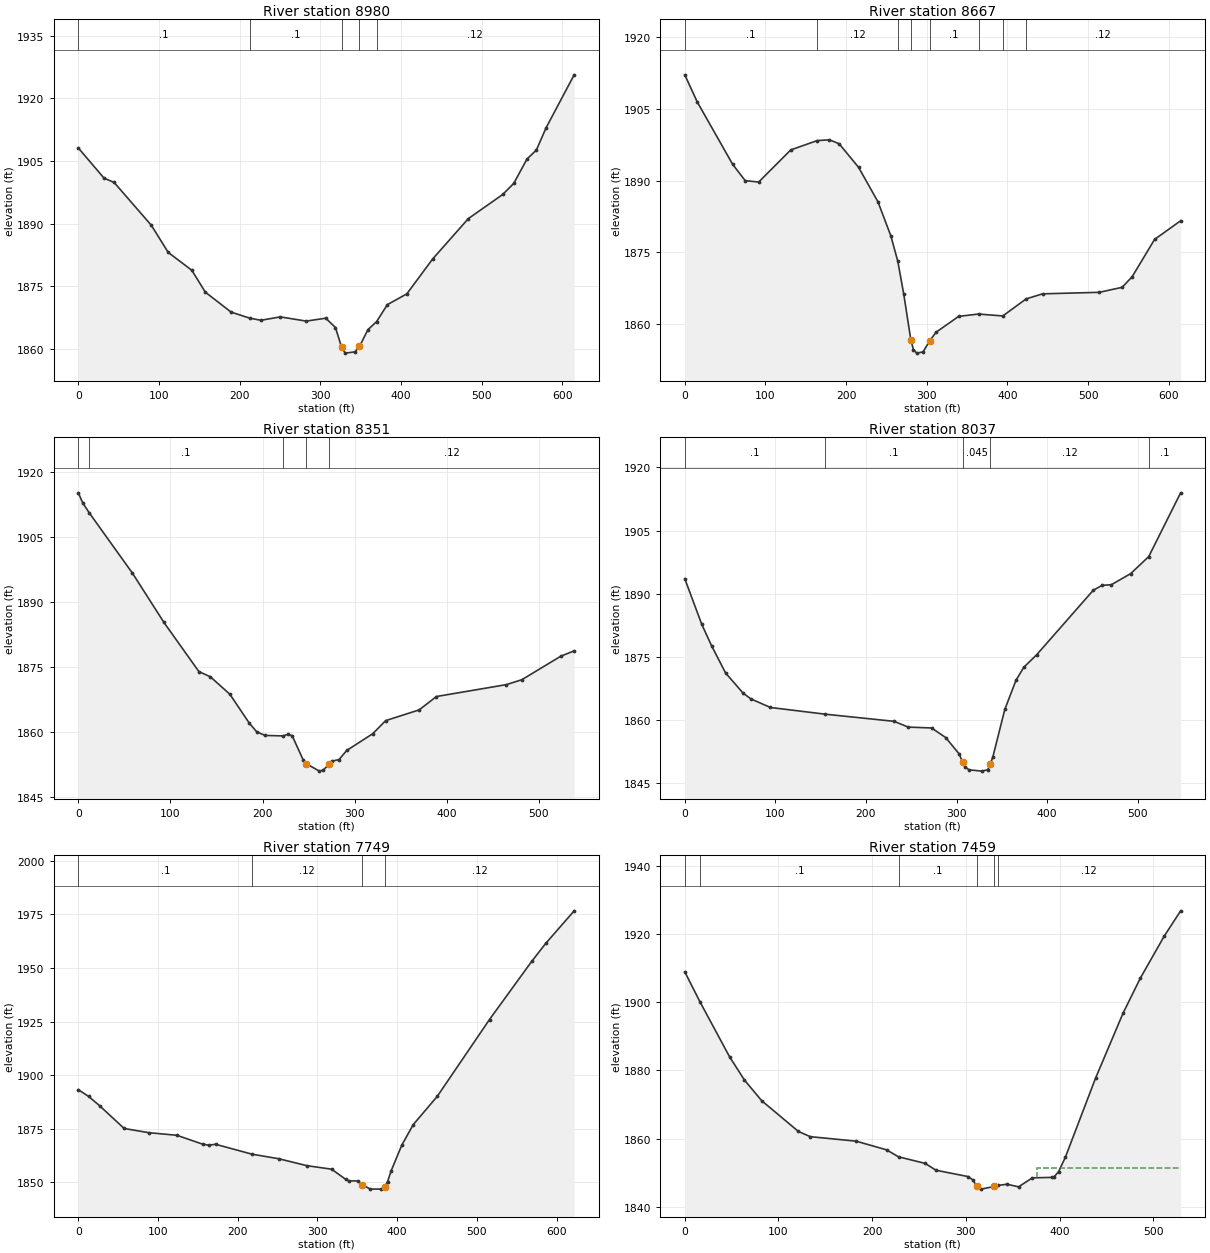
Type RM Length L Ch R = 1 ,8980    ,312.7,312.7,312.7
XS GIS Cut Line= 3
2460152.32349315562603.4905755432460317.65338734562552.531270599
2460757.33372663 562592.48623764
#Sta/Elev= 30
       0 1908.12    31.8 1900.89    44.4 1899.84    90.4 1889.59   111.4 1883.07
   140.7 1878.77   157.4 1873.53   189.3 1868.76  212.361867.298   226.3 1866.79
   250.4  1867.6   282.5 1866.59   306.6 1867.29   318.7 1865.05   326.2 1860.35
   330.7 1858.91   342.8 1859.22  348.46 1860.51   358.9 1864.54  369.631866.462
     383 1870.54   407.1 1873.12   439.2 1881.51   483.4 1891.18     526 1896.97
   539.6 1899.61     556 1905.45   567.7 1907.63   579.8 1912.99   614.5 1925.66
#Mann= 5 ,-1 , 0
       0      .1       0  212.36      .1       0   326.2    .045       0
  348.46      .1       0  369.63     .12       0
Bank Sta=326.2,348.46
XS Rating Curve= 0 ,0
Exp/Cntr=0.3,0.1

Type RM Length L Ch R = 1 ,8667    ,315.6,315.6,315.6
XS GIS Cut Line= 3
2460143.44649315562878.2962032962460559.71757831562861.807559064
 2460728.5539464562757.952188202
#Sta/Elev= 30
       0 1912.16    15.3 1906.52    59.3  1893.4    74.9 1889.97    91.6 1889.68
   131.4 1896.42   164.11898.365   179.4 1898.54   191.4  1897.7   215.5 1892.76
   239.5 1885.54   255.5 1878.39  264.161873.027   271.5 1866.16   280.3 1856.57
   283.5 1854.55   287.5 1853.81   295.5 1854.07   303.5 1856.37   311.5 1858.18
   339.6 1861.52  364.211862.006  394.331861.605  423.171865.178   443.6 1866.24
     514 1866.56   542.3 1867.61   554.7 1869.83   582.5 1877.65   614.8 1881.56
#Mann= 8 ,-1 , 0
       0      .1       0   164.1     .12       0  264.16      .1       0
   280.3    .045       0   303.5      .1       0  364.21     .12       0
  394.33      .1       0  423.17     .12       0
Bank Sta=280.3,303.5
XS Rating Curve= 0 ,0
Exp/Cntr=0.3,0.1

Type RM Length L Ch R = 1 ,8351    ,314.7,314.7,314.7
XS GIS Cut Line= 2
2460572.24278022563298.5338282772460747.03069644562789.279148315
#Sta/Elev= 30
       0 1915.28     4.8 1912.94   11.721910.701    58.8 1896.72      93 1885.34
   130.9 1874.01   143.4  1872.8   164.6 1868.76   185.7 1862.08   193.7  1860.1
   202.6 1859.27  222.211859.149     228 1859.55   232.2 1859.18   244.1 1853.64
   247.3 1852.75   261.8 1851.02   266.1 1851.28   272.5  1852.7   275.6 1853.35
     283 1853.67   291.4 1855.79   319.7 1859.66   333.7 1862.68   370.1 1865.16
   388.9 1868.25   464.8 1870.99   481.7 1872.14     524 1877.57   538.4 1878.79
#Mann= 5 ,-1 , 0
       0      .1       0   11.72      .1       0  222.21      .1       0
   247.3    .045       0   272.5     .12       0
Bank Sta=247.3,272.5
XS Rating Curve= 0 ,0
Exp/Cntr=0.3,0.1

Type RM Length L Ch R = 1 ,8037    ,287.8,287.8,287.8
XS GIS Cut Line= 2
2460659.91717034563402.7518969662461083.41618404563055.944137378
#Sta/Elev= 30
       0 1893.56    18.7 1882.73    29.5 1877.66      45 1871.18    64.4 1866.37
      73 1865.01    94.5 1862.97  155.241861.372   231.1 1859.68   246.6 1858.31
   272.5  1858.1     288 1855.83   302.8 1851.96   306.7 1850.02   309.1 1848.88
   313.9 1848.16   328.1 1847.85   334.5 1848.19   337.3 1849.49   340.2 1851.31
   353.3 1862.51   365.7 1869.46   374.3 1872.53   388.5  1875.5     451 1890.83
   460.7 1891.98   470.9 1892.13   492.2 1894.76  512.231898.826   547.4 1913.96
#Mann= 5 ,-1 , 0
       0      .1       0  155.24      .1       0   306.7    .045       0
   337.3     .12       0  512.23      .1       0
Bank Sta=306.7,337.3
XS Rating Curve= 0 ,0
Exp/Cntr=0.3,0.1

Type RM Length L Ch R = 1 ,7749    ,289.8,289.8,289.8
XS GIS Cut Line= 2
2460714.52267858563592.3254065922461279.12538734563331.326424457
#Sta/Elev= 30
       0 1893.23      13 1890.03    26.7 1885.72    57.5 1875.09    88.6 1873.12
   123.6 1871.92   155.9 1867.77   163.3 1867.29   172.1 1867.72  218.091863.078
   251.3 1860.98   286.7 1857.73   317.7 1856.09   335.2 1851.41   339.6 1850.64
   350.8 1850.58   356.1 1848.83     366 1846.85   379.2 1846.78   383.6 1847.13
   384.7 1847.85     388 1850.32   392.4 1855.31   405.7 1867.26   420.1 1876.88
   450.3 1890.11   515.8 1925.97   568.7 1953.09   586.3 1961.49     622 1976.71
#Mann= 4 ,-1 , 0
       0      .1       0  218.09     .12       0   356.1    .045       0
   384.7     .12       0
Bank Sta=356.1,384.7
XS Rating Curve= 0 ,0
Exp/Cntr=0.3,0.1

Type RM Length L Ch R = 1 ,7459    ,286.8,286.8,286.8
XS GIS Cut Line= 2
2460855.27501619563864.6937542662461316.20632842563604.644491469
#Sta/Elev= 30
       0 1908.85   16.411899.955    47.9  1883.9    63.7 1877.13    82.1 1871.08
   121.3 1862.07   133.9 1860.55     183 1859.22   215.3 1856.69  228.091854.645
   256.6 1852.71   268.1 1850.71   302.5 1848.84   307.1 1847.94   311.7 1846.06
   316.3 1845.17   330.1 1845.95  333.93 1846.24   343.8 1846.61   356.2 1845.84
   370.9 1848.47   391.4 1848.61   394.4 1848.84     399 1850.32   406.1 1854.46
   438.4 1877.69   467.8 1896.77   486.2 1907.01   511.8 1919.37   529.2 1926.74
#Mann= 6 ,-1 , 0
       0      .1       0   16.41      .1       0  228.09      .1       0
   311.7    .045       0   330.1      .1       0  333.93     .12       0
#XS Ineff= 2 , 0
                          376.17         1851.47
Permanent Ineff=
       F       F
Bank Sta=311.7,330.1
XS Rating Curve= 0 ,0
Exp/Cntr=0.3,0.1

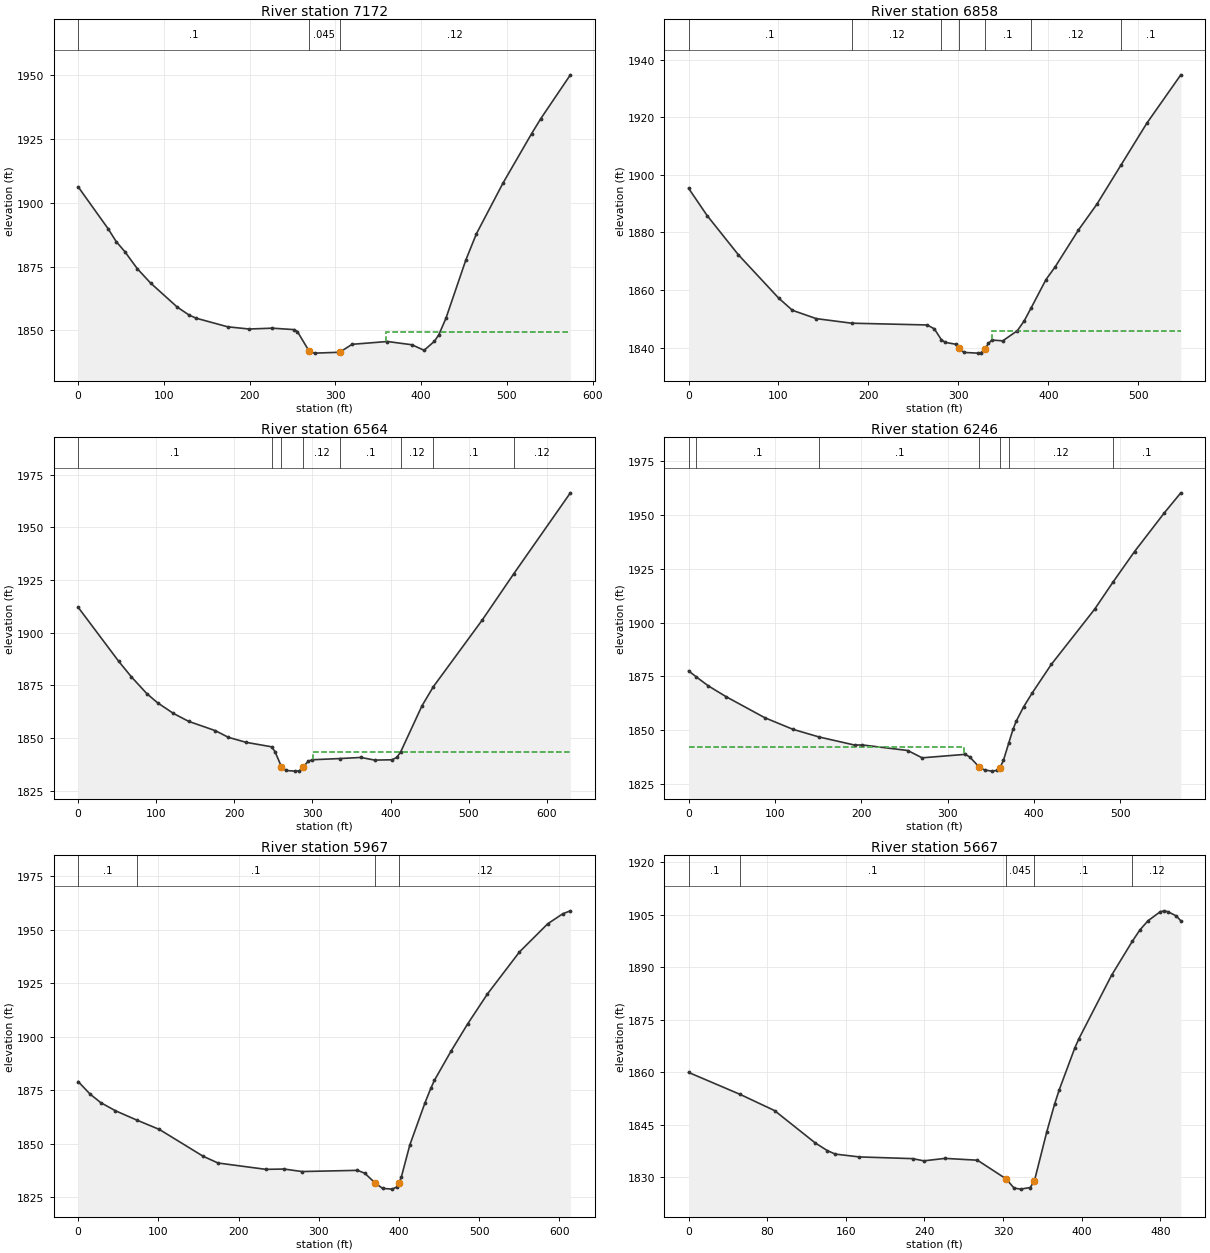
Type RM Length L Ch R = 1 ,7172    ,314.1,314.1,314.1
XS GIS Cut Line= 2
2460979.22290142564112.3458690392461438.44341024563767.777245443
#Sta/Elev= 30
       0 1906.28      35  1889.8    44.4 1884.78    54.4 1880.86    69.1  1874.1
    84.4 1868.55   115.7 1859.05   129.4 1855.96   137.8 1854.71   174.4 1851.35
   199.4 1850.48   226.4 1850.81   252.1 1850.24   255.7  1849.5   269.4  1841.8
   275.7 1841.02     3051841.359   319.5 1844.48   360.7 1845.58   389.3  1844.3
   403.5 1842.13   415.6 1845.69   420.7 1848.26     429 1854.74   452.1  1877.5
   464.5 1887.85   495.6  1907.8   528.9 1927.15   539.5 1932.98   574.1 1950.21
#Mann= 3 ,-1 , 0
       0      .1       0   269.4    .045       0     305     .12       0
#XS Ineff= 2 , 0
                          359.55         1849.48
Permanent Ineff=
       F       F
Bank Sta=269.4,305
XS Rating Curve= 0 ,0
Exp/Cntr=0.3,0.1

Type RM Length L Ch R = 1 ,6858    ,293.8,293.8,293.8
XS GIS Cut Line= 3
 2461047.4693767564194.4892460262461217.21368893 564124.35616392
2461580.47765626564105.768229255
#Sta/Elev= 30
       0 1895.29    20.6 1885.83    55.5 1872.16   100.2 1857.16   115.5 1852.92
     142 1850.03  181.241848.444   265.3 1847.83   273.3 1846.48   281.21842.678
   285.3  1841.8   297.3 1841.13   300.8 1839.79   306.1  1838.3   321.4 1838.05
   325.4 1838.24   329.4 1839.39   333.4 1841.41   337.4 1842.58   349.4 1842.32
   365.6 1845.83   373.2 1849.22  381.121853.847   397.5 1863.61   407.5 1867.92
   433.5 1880.77   453.9 1889.68  481.04 1903.43   509.6 1917.88   547.4 1934.68
#Mann= 7 ,-1 , 0
       0      .1       0  181.24     .12       0   281.2      .1       0
   300.8    .045       0   329.4      .1       0  381.12     .12       0
  481.04      .1       0
#XS Ineff= 2 , 0
                          337.33         1845.88
Permanent Ineff=
       F       F
Bank Sta=300.8,329.4
XS Rating Curve= 0 ,0
Exp/Cntr=0.3,0.1

Type RM Length L Ch R = 1 ,6564    ,318.8,318.8,318.8
XS GIS Cut Line= 3
2461214.86504356564583.4957260882461522.95471352564274.977165693
2461698.99340727 564192.94633992
#Sta/Elev= 30
       0 1912.07    51.7 1886.55    68.2 1879.07      88  1871.1   101.7 1866.78
     122 1861.75   141.3 1858.01   175.7 1853.57   192.3 1850.42   214.9 1848.05
  247.821845.905   252.1 1843.57   260.2 1836.53   266.2 1834.69   277.8 1834.39
   283.2 1834.51   288.5 1836.58   294.5 1839.04   299.9 1839.79  335.581840.359
   362.1 1840.88   379.6 1839.62   401.7 1839.77   407.9 1840.86   412.91843.506
   440.2 1865.35  454.611874.341   517.2 1905.95  557.811928.011   630.2 1966.32
#Mann= 8 ,-1 , 0
       0      .1       0  247.82     .12       0   260.2    .045       0
   288.5     .12       0  335.58      .1       0   412.9     .12       0
  454.61      .1       0  557.81     .12       0
#XS Ineff= 2 , 0
                          300.35         1843.53
Permanent Ineff=
       F       F
Bank Sta=260.2,288.5
XS Rating Curve= 0 ,0
Exp/Cntr=0.3,0.1

Type RM Length L Ch R = 1 ,6246    ,278.4,278.4,278.4
XS GIS Cut Line= 2
2461415.43254917564787.9311432422461827.12224293564393.858273912
#Sta/Elev= 30
       0 1877.61    9.111874.752    22.9 1870.64    43.3 1865.67    88.3 1855.88
   120.9 1850.51  151.311846.953   192.4 1843.21   201.1 1843.28   253.8  1840.7
   270.4 1837.31   320.2 1838.92   325.4 1837.77   336.8 1832.91   342.8 1831.66
   351.1 1831.15   356.7 1831.47   360.2 1832.56   364.5 1836.08   370.81844.295
   375.6 1850.47   379.3 1854.26   387.8 1860.85   397.7 1867.27   419.9 1880.55
   470.1 1906.14  491.371918.706   516.3 1932.86     551 1950.89   569.9 1960.08
#Mann= 7 ,-1 , 0
       0      .1       0    9.11      .1       0  151.31      .1       0
   336.8    .045       0   360.2      .1       0   370.8     .12       0
  491.37      .1       0
#XS Ineff= 2 , 0
          319.06 1842.24
Permanent Ineff=
       F       F
Bank Sta=336.8,360.2
XS Rating Curve= 0 ,0
Exp/Cntr=0.3,0.1

Type RM Length L Ch R = 1 ,5967    ,300.5,300.5,300.5
XS GIS Cut Line= 2
 2461482.1645604564962.0843848232462018.97605613564664.771153121
#Sta/Elev= 30
       0    1879    14.8 1873.14    28.1 1869.15    46.4 1865.34   73.131860.971
   101.3 1856.58   156.1 1843.99   174.4  1840.9   233.9 1837.94   256.7 1838.08
     279 1836.91   348.2 1837.47   357.3 1836.12   369.9 1831.68   379.4 1829.05
   391.2 1828.69   397.1 1829.63     400 1831.55     403 1834.55   413.5  1849.4
   432.4 1869.09   439.6 1875.81   444.2 1879.63   464.8 1893.19   485.4 1905.85
   510.2 1919.93   550.1 1939.56   585.4 1952.75   604.2 1957.43   613.6 1958.79
#Mann= 4 ,-1 , 0
       0      .1       0   73.13      .1       0   369.9    .045       0
     400     .12       0
Bank Sta=369.9,400
XS Rating Curve= 0 ,0
Exp/Cntr=0.3,0.1

Type RM Length L Ch R = 1 ,5667    ,272.3,272.3,272.3
XS GIS Cut Line= 2
2461626.07929488565125.9062951732462111.04624661565000.473688348
#Sta/Elev= 30
       0 1859.96   52.521853.682    87.5 1849.07   128.8 1839.86   141.2 1837.65
   149.4 1836.65   173.7 1835.85   227.9 1835.36   239.4 1834.73     261 1835.43
     294 1834.91     323 1829.61   331.2 1826.97   337.8 1826.66   347.7 1827.12
   351.9 1828.98   364.5 1842.99   372.5 1850.95   377.2 1855.01   393.2 1867.06
   397.3 1869.63   430.4 1887.65  451.491897.341   459.3 1900.63   467.6 1903.24
     480  1905.8   484.1 1906.06   488.2 1905.76   496.5 1904.57   500.9 1903.21
#Mann= 5 ,-1 , 0
       0      .1       0   52.52      .1       0     323    .045       0
   351.9      .1       0  451.49     .12       0
Bank Sta=323,351.9
XS Rating Curve= 0 ,0
Exp/Cntr=0.3,0.1