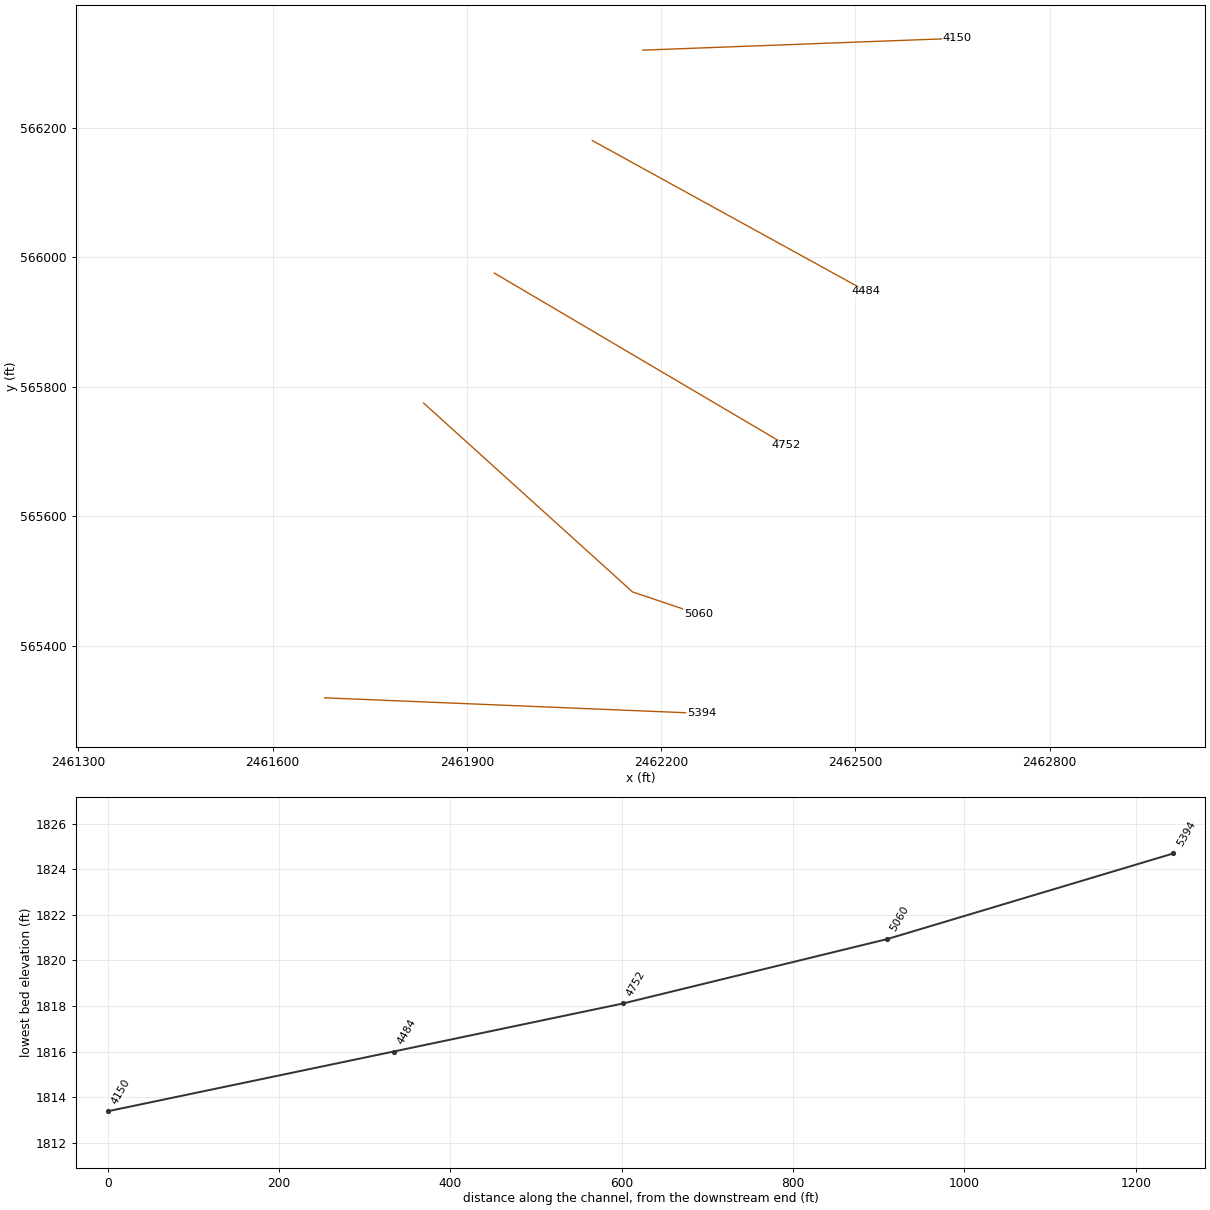
HEC-RAS study LICKRN.prj: LICKRN

--- LICKRN.g01 (geometry) --- (continued)

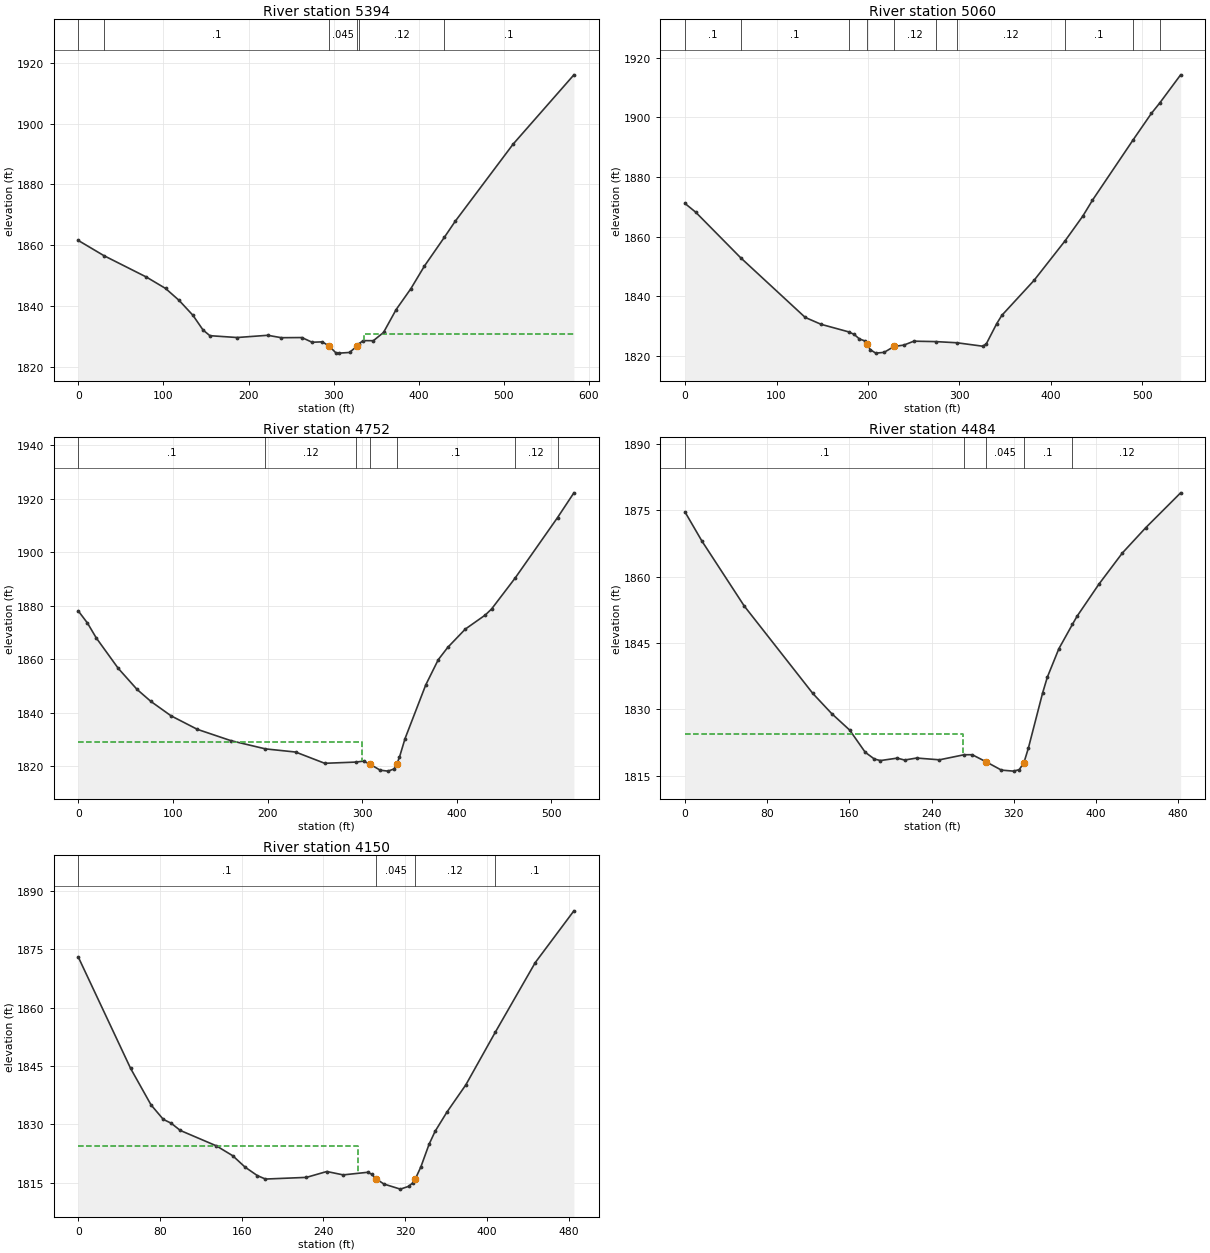
Type RM Length L Ch R = 1 ,5394    ,334.4,334.4,334.4
XS GIS Cut Line= 2
2461680.30916363565319.5502786932462262.22341024565295.518786933
#Sta/Elev= 30
       0 1861.64   29.981856.679    79.9 1849.66   102.5 1845.91   118.5 1841.97
   134.6 1837.13   146.6 1832.27   154.6 1830.41   186.6 1829.81   222.6 1830.54
   238.6 1829.75   262.7  1829.8   274.7 1828.26   286.7 1828.39   294.7 1827.02
   302.7 1824.78   306.7 1824.69   318.7 1824.91   327.6 1827.03  330.071827.817
   334.7  1828.8   346.7 1828.76   358.7 1831.48   373.5 1838.98   390.8 1845.83
   406.8 1853.28   430.11862.654   442.8 1867.89   510.9 1893.22   582.4 1915.97
#Mann= 6 ,-1 , 0
       0      .1       0   29.98      .1       0   294.7    .045       0
   327.6      .1       0  330.07     .12       0   430.1      .1       0
#XS Ineff= 2 , 0
                           335.3         1830.91
Permanent Ineff=
       F       F
Bank Sta=294.7,327.6
XS Rating Curve= 0 ,0
Exp/Cntr=0.3,0.1

Type RM Length L Ch R = 1 ,5060    ,308,308,308
XS GIS Cut Line= 3
2461833.25879809565774.6938447572462155.88330771565483.064336517
2462257.33747586565448.910245735
#Sta/Elev= 30
       0 1871.11    11.6 1868.21   60.681852.952   131.4  1832.9   148.8 1830.59
  178.971828.053     185 1827.19   190.7 1825.68   196.3 1825.07   199.2 1823.88
   202.5  1822.1   208.5 1820.93   217.7 1821.19   228.5 1823.16   239.3 1823.63
   250.2 1824.94  274.291824.794  297.261824.407   325.5 1823.25   329.4 1824.04
   340.8 1830.82   346.4  1833.6   381.5 1845.29  415.551858.597   434.9 1866.87
   445.5 1872.22   490.21892.563   509.9 1901.32   519.11904.835   541.9 1914.26
#Mann= 10 ,-1 , 0
       0      .1       0   60.68      .1       0  178.97     .12       0
   199.2    .045       0   228.5     .12       0  274.29      .1       0
  297.26     .12       0  415.55      .1       0   490.2     .12       0
   519.1      .1       0
Bank Sta=199.2,228.5
XS Rating Curve= 0 ,0
Exp/Cntr=0.3,0.1

Type RM Length L Ch R = 1 ,4752    ,268,268,268
XS GIS Cut Line= 2
2461942.36117034565975.5329986142462393.65236948565709.448271985
#Sta/Elev= 30
       0 1878.04     9.7  1873.5      19 1867.94    42.2 1856.57    62.1 1848.68
    76.7  1844.2      98 1838.81   125.8 1833.75   161.4  1829.5  197.861826.432
   229.7 1825.25   260.5 1821.04  293.421821.494   301.6 1821.86   308.4 1820.68
   319.2 1818.45   327.4 1818.11   333.8 1818.93   336.7 1820.82   339.4 1823.22
   345.4  1830.3   367.3 1850.39   380.5 1859.81   390.5  1864.4   409.1 1871.26
   430.2 1876.52   436.9  1878.8  461.681890.312  506.64 1913.01   523.9 1922.25
#Mann= 7 ,-1 , 0
       0      .1       0  197.86     .12       0  293.42      .1       0
   308.4    .045       0   336.7      .1       0  461.68     .12       0
  506.64      .1       0
#XS Ineff= 2 , 0
          299.72 1829.13
Permanent Ineff=
       F       F
Bank Sta=308.4,336.7
XS Rating Curve= 0 ,0
Exp/Cntr=0.3,0.1

Type RM Length L Ch R = 1 ,4484    ,333.7,333.7,333.7
XS GIS Cut Line= 2
2462093.73769644566180.1798296632462516.50357277565947.560934082
#Sta/Elev= 30
       0  1874.6    16.4 1868.05    57.6 1853.36   124.4 1833.57   142.7 1829.03
   160.3 1825.28   175.4 1820.27   184.3 1818.74   190.2 1818.39   206.6 1818.94
   213.7 1818.51   225.5 1818.96   247.7 1818.56  271.761819.708   279.6 1819.71
   293.1 1818.11     308 1816.23   319.8    1816   325.3 1816.33   329.9 1817.89
   334.3 1821.24   348.1 1833.66   352.7 1837.24   363.9 1843.67   377.21849.222
   381.6 1851.01   402.9 1858.28   425.8 1865.35   448.6 1871.08   482.5 1878.95
#Mann= 5 ,-1 , 0
       0      .1       0  271.76     .12       0   293.1    .045       0
   329.9      .1       0   377.2     .12       0
#XS Ineff= 2 , 0
          270.46 1824.43
Permanent Ineff=
       F       F
Bank Sta=293.1,329.9
XS Rating Curve= 0 ,0
Exp/Cntr=0.3,0.1

Type RM Length L Ch R = 1 ,4150    ,305.8,305.8,305.8
XS GIS Cut Line= 2
2462171.62876513566319.7927967042462656.51897936566338.023355768
#Sta/Elev= 30
       0 1873.02    51.2 1844.41    71.2 1835.03    83.2 1831.31    90.9 1830.33
    99.8 1828.47   135.2  1824.5   151.2 1821.96   163.2 1819.05   175.2 1816.87
   183.2 1815.97   223.3  1816.4   243.3 1817.91   259.3 1817.04   283.3 1817.71
   287.3  1817.2   291.2 1816.07   299.3 1814.68   315.3 1813.38   323.3 1814.09
   327.3 1814.96     330 1816.04   335.4 1819.12   343.4 1824.91   349.3 1828.24
   360.9 1833.19   379.4 1840.19  408.09 1853.65   447.4 1871.63   485.2 1884.92
#Mann= 4 ,-1 , 0
       0      .1       0   291.2    .045       0     330     .12       0
  408.09      .1       0
#XS Ineff= 2 , 0
          273.44  1824.5
Permanent Ineff=
       F       F
Bank Sta=291.2,330
XS Rating Curve= 0 ,0
Exp/Cntr=0.3,0.1
LCMann Table=0

Chan Stop Cuts=-1
Use User Specified Reach Order=0
Composite Channel Slope=5